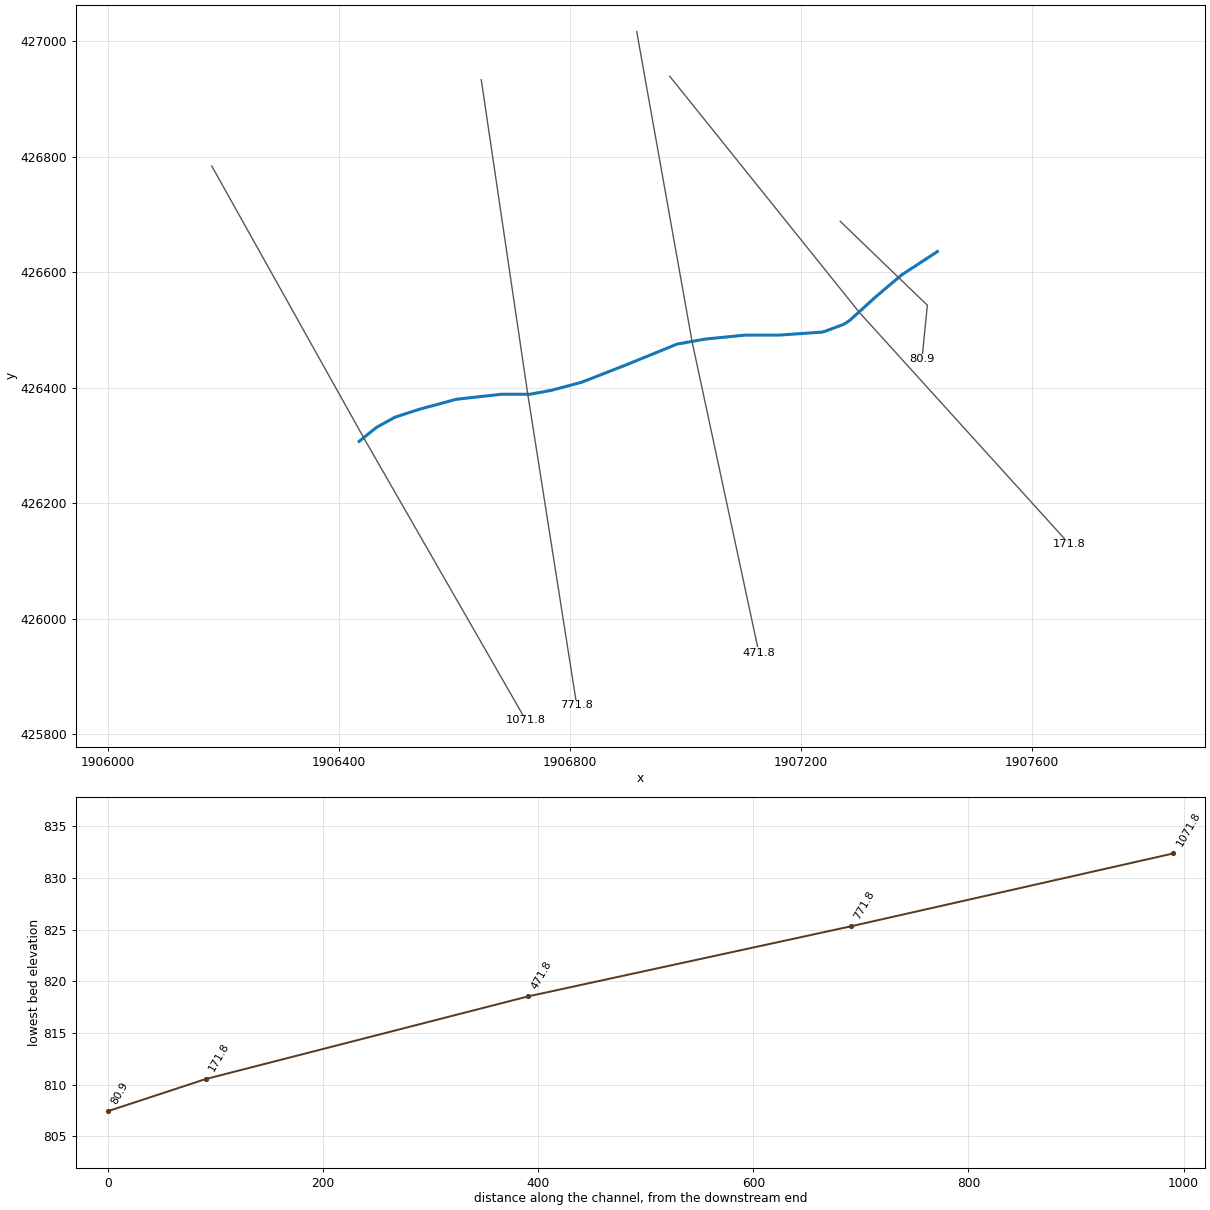
--- LFkScrblCk.prj (project) ---

Proj Title=LFkScrblCk
Current Plan=p01
Geom File=g01
Flow File=f01
Plan File=p01
DSS Export Rating Curves=0
DSS Export Rating Curve Sorted=0
DSS Export Volume Flow Curves=0
DXF OffsetX=0
DXF OffsetY=0
DXF ScaleX=0
DXF ScaleY=0

--- LFkScrblCk.p01 (plan) ---

Plan Title=Floodplain
Program Version=4.00
Geom File=g01
Flow File=f01
K Sum by GR=0
Std Step Tol=0.01
Critical Tol=0.01
Num of Std Step Trials=20
Max Error Tol=0.3
Flow Tol Ratio=0.001
Split Flow NTrial=30
Split Flow Tol=0.02
Split Flow Ratio=0.02
Log Output Level=0
Friction Slope Method=1
Unsteady Friction Slope Method=2
Unsteady Bridges Friction Slope Method=1
Global Log Level=0
CheckData=False
Run HTab=0
Run UNet=0
Run PostProcess=0
UNET Theta=0
UNET Theta Warmup=0
UNET ZTol=0
UNET ZSATol=0
UNET MxIter=0
UNET MaxInSteps=0
UNET DtIC=0
UNET DtMin=0
UNET MaxCRTS=0
UNET WFStab=0
UNET SFStab=0
UNET WFX=0
UNET SFX=0
UNET DSS MLevel=0
UNET DZMax Abort=0
UNET Convert EG Bridges=0
UNET Use Existing IB Tables=0
UNET Froude Limit=0
UNET Froude Power=0
Write IC File=0
Echo Input=False
Echo Output=False
Write Detailed=0

--- LFkScrblCk.f01 (steady flow) ---

Flow Title=NFF Regression Equation
Program Version=4.00
Number of Profiles=1
Profile Names=P100yr
River Rch & RM=LFkScrblCk,Main      ,1071.8
513.5255
River Rch & RM=LFkScrblCk,Main      ,171.8
522.9524
Boundary for River Rch & Prof#=LFkScrblCk,Main      ,1
Up Type=0
Dn Type=3
Dn Slope=0.027828

--- LFkScrblCk.g01 (geometry) ---

Geom Title=USGS 3m DEM
Program Version=4.00

River Reach=LFkScrblCk     ,Main
Reach XY= 21
     1906434.731      426307.345     1906464.893      426331.707
     1906497.359      426349.462     1906538.897      426362.901
     1906603.134      426380.262     1906681.258      426388.942
     1906730.500      426388.942     1906767.370      426395.702
     1906820.147      426409.776     1906900.009      426441.026
     1906985.078      426475.748     1907033.689      426484.429
     1907103.134      426491.373     1907162.161      426491.373
     1907236.814      426496.581     1907240.481      426497.629
     1907273.108      426509.726     1907283.585      426516.344
     1907328.828      426557.345     1907373.967      426595.540
     1907435.934      426636.007

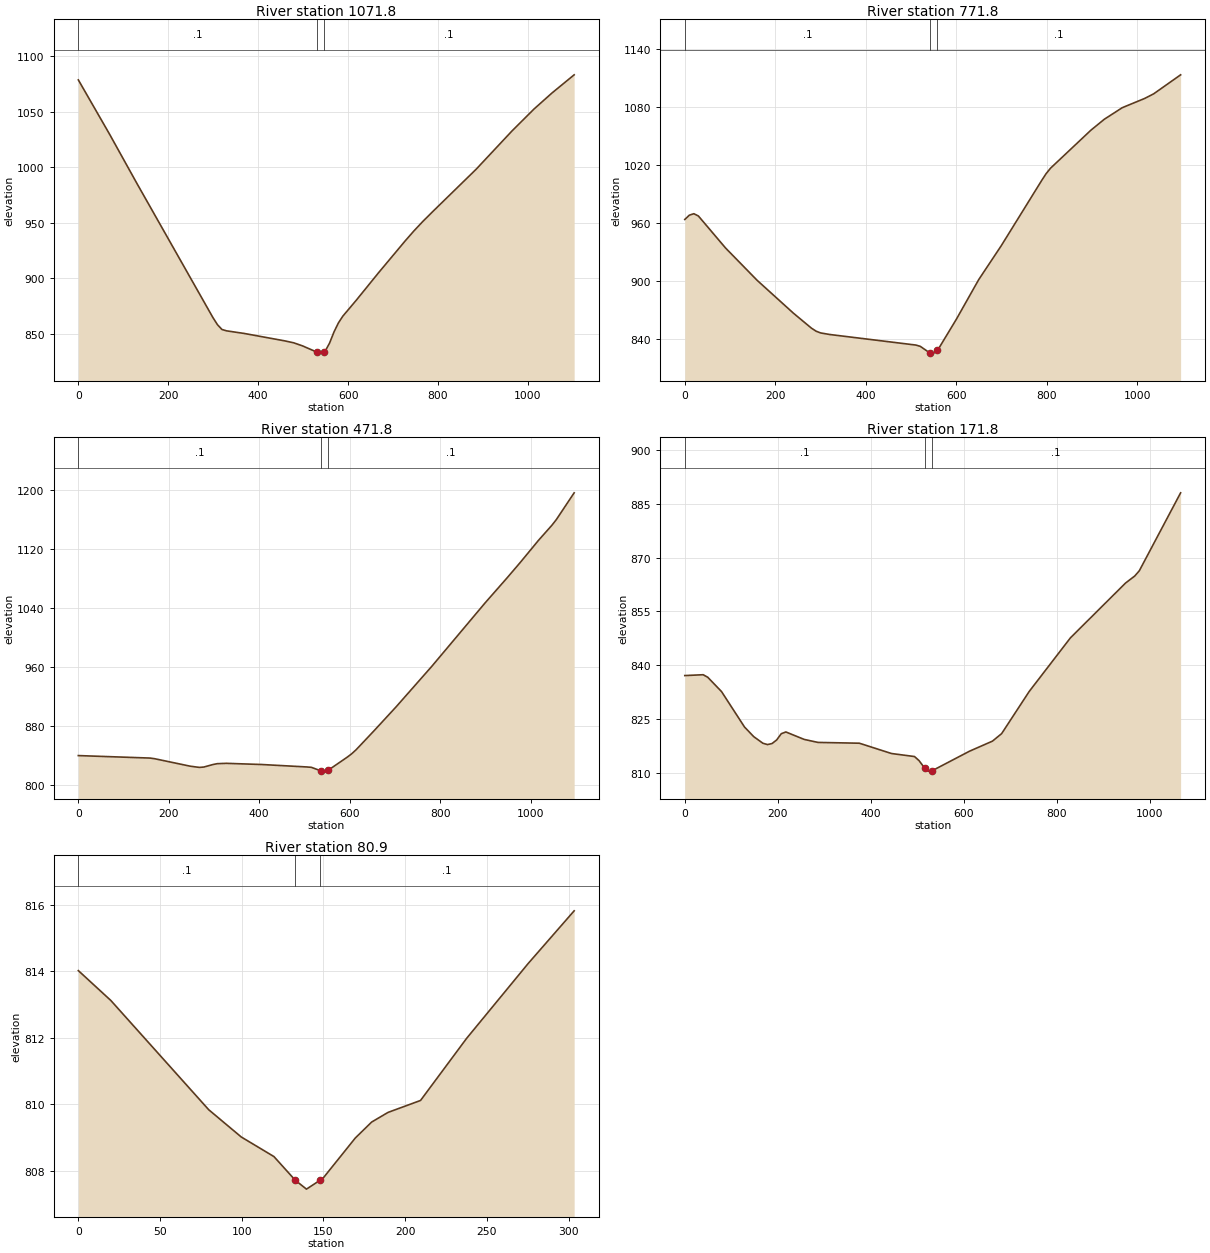
Type RM Length L Ch R = 1 ,1071.8,308.1,300,291.8
XS GIS Cut Line= 3
     1906179.495      426784.114     1906442.510      426313.629
     1906723.265      425824.636
#Sta/Elev= 30
       0 1078.68    69.9 1029.43   129.8  985.72   299.4  864.43   309.4  858.08
   319.4  853.72   329.4  852.50   369.3  850.10   459.2  843.44   479.1  841.69
   499.1  838.86   531.5  833.14   539.0  832.39   546.5  833.62   548.9  834.02
   558.8  841.41   568.7  851.48   578.6  859.68   588.5  865.79   618.2  880.04
   667.6  904.74   727.0  933.53   746.8  942.69   766.5  951.17   786.3  959.17
   885.2  998.27   964.4 1032.55  1013.8 1052.49  1053.4 1066.80  1102.9 1083.25
#Mann= 3 , 0 , 0
       0     0.1       0   531.5   0.045       0   546.5     0.1       0
Bank Sta=   531.5,   546.5
Exp/Cntr=0.3,0.1

Type RM Length L Ch R = 1 ,771.8,299.3,299.9,301.2
XS GIS Cut Line= 3
     1906646.115      426933.512     1906726.678      426388.942
     1906811.489      425850.084
#Sta/Elev= 30
       0  963.80    10.0  968.22    20.0  969.76    30.0  967.42    90.1  934.23
   160.1  900.66   240.2  866.67   280.2  851.10   290.3  848.04   300.3  846.25
   320.3  844.64   510.5  833.70   520.5  832.37   540.5  825.88     543  825.74
   550.5  825.33     558  828.50   560.4  829.51   600.1  860.28   649.7  901.48
   699.3  936.44   788.5 1003.91   798.4 1011.09   808.4 1016.88   897.6 1056.23
   927.4 1067.63   967.0 1079.59  1016.6 1089.17  1036.5 1093.96  1096.0 1113.63
#Mann= 3 , 0 , 0
       0     0.1       0     543   0.045       0     558     0.1       0
Bank Sta=     543,     558
Exp/Cntr=0.3,0.1

Type RM Length L Ch R = 1 ,471.8,288.3,299.7,311.7
XS GIS Cut Line= 3
     1906915.283      427016.944     1907011.098      426480.394
     1907126.850      425941.226
#Sta/Elev= 30
       0  839.65   158.6  836.27   168.5  835.43   247.7  825.22   267.6  823.60
   277.5  824.09   297.3  827.43   307.2  828.66   327.0  829.13   406.3  827.51
   505.4  824.20   515.3  823.72   535.1  819.21   537.5  819.05   545.0  818.55
   552.5  820.22   554.9  820.76   594.3  837.33   604.1  841.89   614.0  847.36
   653.4  872.95   702.6  905.69   781.4  960.58   899.5 1046.83   948.8 1081.29
   978.3 1102.49  1017.7 1131.83  1047.2 1152.20  1057.1 1159.97  1096.5 1196.28
#Mann= 3 , 0 , 0
       0     0.1       0   537.5   0.045       0   552.5     0.1       0
Bank Sta=   537.5,   552.5
Exp/Cntr=0.3,0.1

Type RM Length L Ch R = 1 ,171.8,88,90.9,92.4
XS GIS Cut Line= 3
     1906972.493      426939.512     1907300.180      426531.383
     1907664.561      426129.305
#Sta/Elev= 30
       0  837.15    39.5  837.38    49.4  836.67    79.0  832.69   128.4  822.83
   148.1  820.16   167.9  818.31   177.8  817.94   187.6  818.23   197.5  819.23
   207.4  820.96   217.3  821.45   256.8  819.37   286.4  818.54   375.3  818.32
   444.4  815.45   493.8  814.61   503.6  813.48   515.9  811.35   523.4  810.55
   530.9  810.60   612.2  816.10   661.5  818.90   681.2  820.99   740.4  832.71
   829.2  847.66   947.6  862.90   967.4  864.86   977.2  866.32  1066.0  888.01
#Mann= 3 , 0 , 0
       0     0.1       0   515.9   0.045       0   530.9     0.1       0
Bank Sta=   515.9,   530.9
Exp/Cntr=0.3,0.1

Type RM Length L Ch R = 1 ,80.9,86,80.9,75.8
XS GIS Cut Line= 3
     1907267.697      426688.303     1907418.554      426543.056
     1907409.204      426449.549
#Sta/Elev= 16
       0  814.02    19.9  813.12    79.8  809.83    99.7  809.01   119.7  808.42
   132.7  807.71   139.6  807.44   147.7  807.70   149.6  807.76   169.5  808.98
   179.5  809.46   189.5  809.75   209.4  810.11   237.6  811.98   275.2  814.23
   303.4  815.82
#Mann= 3 , 0 , 0
       0     0.1       0   132.7   0.045       0   147.7     0.1       0
Bank Sta=   132.7,   147.7
Exp/Cntr=0.3,0.1